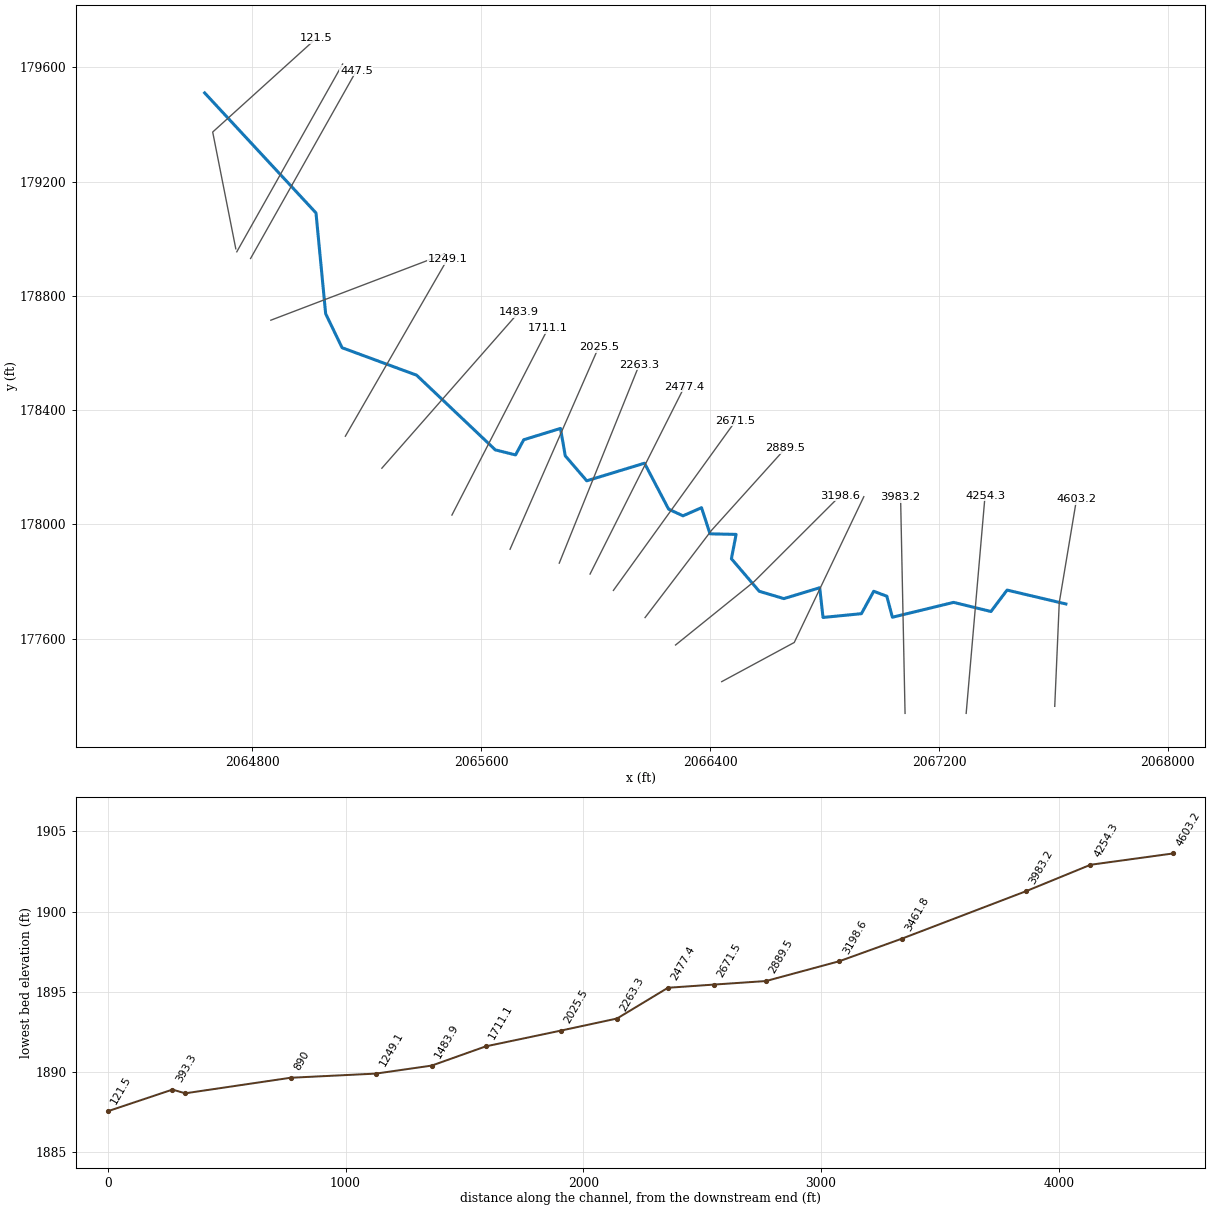
--- LICKRN.prj (project) ---

Proj Title=LICKRN
Current Plan=p01
Default Exp/Contr=0,0
English Units
Geom File=g01
Flow File=f01
Plan File=p01
BEGIN DESCRIPTION:
END DESCRIPTION:
DSS Export Rating Curves= 0
DSS Export Rating Curve Sorted= 0
DSS Export Volume Flow Curves= 0
DXF OffsetX= 0
DXF OffsetY= 0
DXF ScaleX= 0
DXF ScaleY= 0

--- LICKRN.p01 (plan) ---

Plan Title=Floodplain
Program Version=4.00
Geom File=g01
Flow File=f01
K Sum by GR=0
Std Step Tol=0.01
Critical Tol=0.01
Num of Std Step Trials=20
Max Error Tol=0.3
Flow Tol Ratio=0.001
Split Flow NTrial=30
Split Flow Tol=0.02
Split Flow Ratio=0.02
Log Output Level=0
Friction Slope Method=1
Unsteady Friction Slope Method=2
Unsteady Bridges Friction Slope Method=1
Global Log Level=0
CheckData=False
Run HTab=0
Run UNet=0
Run PostProcess=0
UNET Theta=0
UNET Theta Warmup=0
UNET ZTol=0
UNET ZSATol=0
UNET MxIter=0
UNET MaxInSteps=0
UNET DtIC=0
UNET DtMin=0
UNET MaxCRTS=0
UNET WFStab=0
UNET SFStab=0
UNET WFX=0
UNET SFX=0
UNET DSS MLevel=0
UNET DZMax Abort=0
UNET Convert EG Bridges=0
UNET Use Existing IB Tables=0
UNET Froude Limit=0
UNET Froude Power=0
Write IC File=0
Echo Input=False
Echo Output=False
Write Detailed=0

--- LICKRN.f01 (steady flow) ---

Flow Title=2010 USGS WV Regression Equation
Program Version=4.10
Number of Profiles= 1
Profile Names=P100yr
River Rch & RM=LICKRN,Main            ,4603.2
517.5759
River Rch & RM=LICKRN,Main            ,3983.2
  525.35
River Rch & RM=LICKRN,Main            ,447.5
577.4125
River Rch & RM=LICKRN,Main            ,121.5
578.2063
Boundary for River Rch & Prof#=LICKRN,Main            , 1
Up Type= 0
Dn Type= 3
Dn Slope=0.00509
DSS Import GetInterval= 0
DSS Import GetPeak= 0
DSS Import FillOption= 0

--- LICKRN.g01 (geometry) ---

Geom Title=LiDAR
Program Version=4.10

River Reach=LICKRN          ,Main
Reach XY= 30
     2067643.513      177721.199     2067437.957       177769.81
     2067381.707       177694.81     2067251.152      177726.755
     2067037.263      177674.671     2067017.818      177748.282
     2066971.985      177765.643      2066928.93      177687.171
     2066794.902      177673.977     2066783.257      177778.005
     2066658.096      177739.949     2066571.985      177765.643
     2066474.763      177879.532       2066491.1      177964.775
     2066400.075      177966.743     2066370.331      178058.265
     2066305.529      178029.864     2066255.319      178053.143
     2066171.113      178214.081     2065969.207      178152.449
     2065894.207      178239.949     2065877.541      178335.782
     2065749.069      178296.199     2065720.548      178243.049
     2065649.763      178260.782     2065374.684      178522.295
     2065114.303      178618.464     2065056.963      178737.518
     2065023.157       179090.47     2064634.187       179510.64

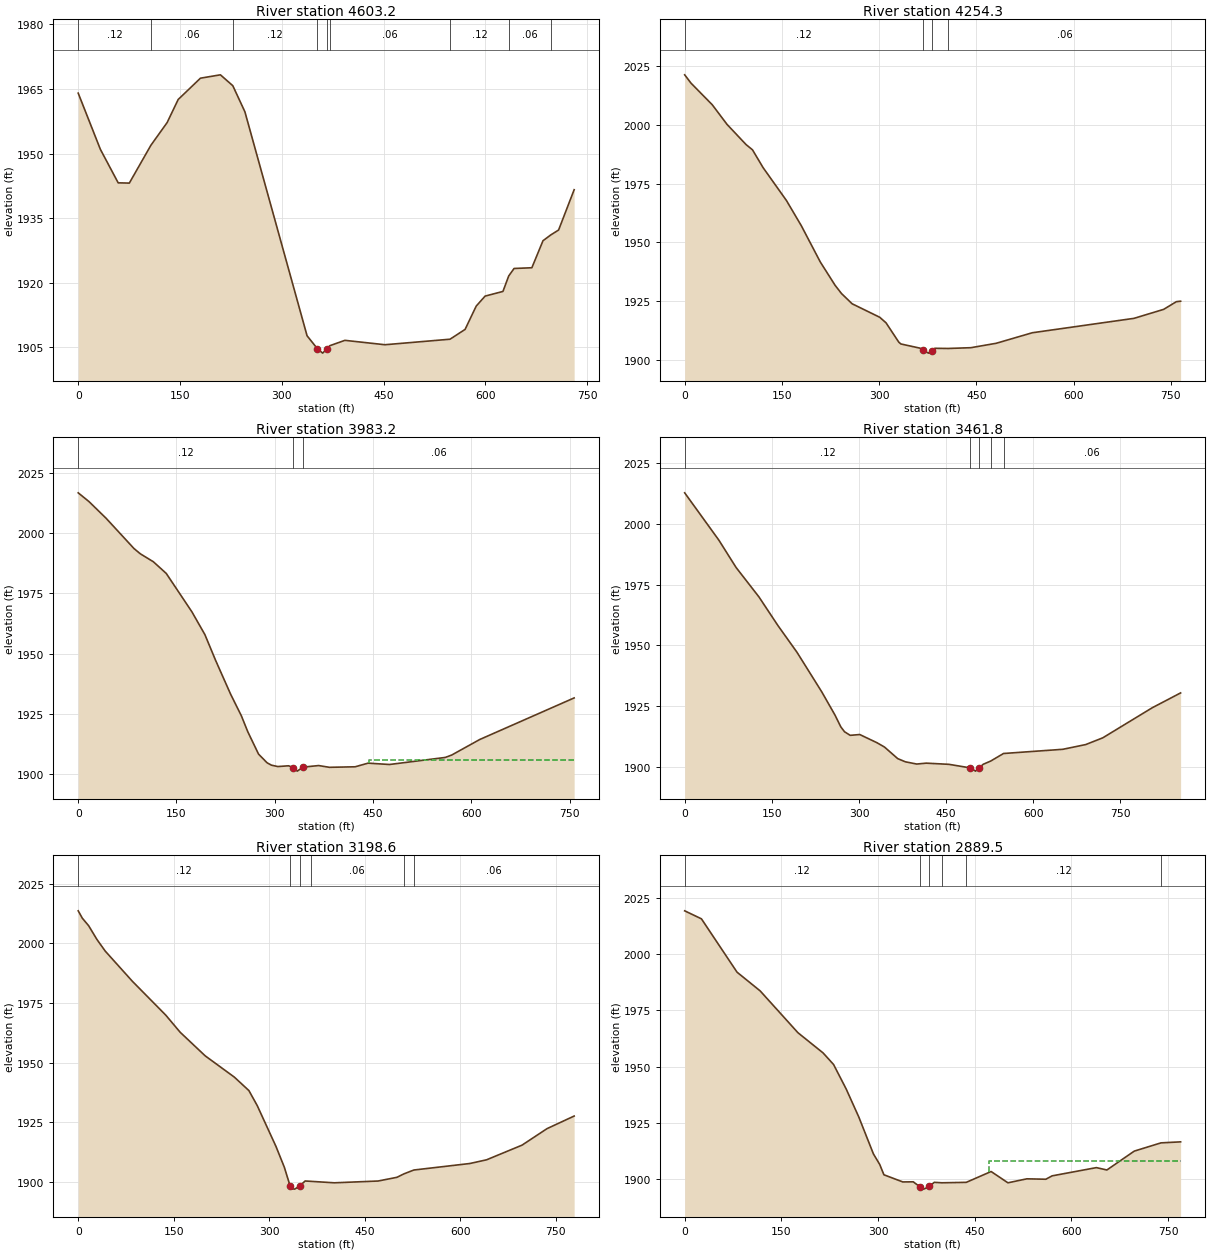
Type RM Length L Ch R = 1 ,4603.2  ,345.8,348.9,350.9
XS GIS Cut Line= 3
      2067604.54      177362.724     2067620.328        177725.8
     2067680.714      178088.095
#Sta/Elev= 30
       0 1964.04    32.7 1950.97    58.9  1943.2    75.3 1943.14  107.221951.963
     131  1957.2   147.3 1962.57   180.1 1967.52   209.5  1968.3  227.771965.774
   245.6 1959.71   337.2 1907.66   352.3 1904.68   360.1 1903.63   366.7 1904.66
  370.681905.353   392.9  1906.6     452 1905.58  547.811906.862     570 1909.14
   586.4 1914.56   599.5 1916.88   625.8 1917.97  634.331921.574   642.2  1923.3
   668.4 1923.47   684.8 1929.75  696.181931.088   707.8 1932.24   730.7  1941.6
#Mann= 9 ,-1 , 0
       0     .12       0  107.22     .06       0  227.77     .12       0
   352.3    .045       0   366.7     .12       0  370.68     .06       0
  547.81     .12       0  634.33     .06       0  696.18     .12       0
Bank Sta=352.3,366.7
XS Rating Curve= 0 ,0
Exp/Cntr=0.3,0.1

Type RM Length L Ch R = 1 ,4254.3  ,266.7,271.1,271.9
XS GIS Cut Line= 2
     2067295.045      177338.085     2067361.017      178100.238
#Sta/Elev= 30
       0 2021.35     9.8  2017.8    42.5 2008.63    65.4 2000.24    94.8 1991.64
   104.6 1989.44     121 1981.84   156.9  1967.9   179.8  1957.2   209.2 1941.71
   232.1 1931.75   241.9 1928.28   258.3 1923.92   300.8 1918.19   310.6 1915.82
   330.2 1907.62   333.5 1906.82   362.9 1905.04  367.931904.131     376 1902.92
  381.03 1904.03   385.8 1904.97  406.671904.905   441.4 1905.23   480.6 1907.11
   536.2 1911.59   693.1 1917.72   738.8 1921.54   758.5 1924.82     765 1925.01
#Mann= 4 ,-1 , 0
       0     .12       0  367.93    .045       0  381.03     .12       0
  406.67     .06       0
Bank Sta=367.93,381.03
XS Rating Curve= 0 ,0
Exp/Cntr=0.3,0.1

Type RM Length L Ch R = 1 ,3983.2  ,531.1,521.4,498.7
XS GIS Cut Line= 2
     2067081.503      177338.085     2067065.878      178095.029
#Sta/Elev= 30
       0 2016.73    16.4 2013.11    42.6 2006.17    85.2  1993.6      95  1991.4
   114.7 1988.14   134.4 1983.29   173.7  1967.3   193.4 1957.91   209.8 1947.19
   232.7 1933.17   249.1 1924.21   258.9  1917.6   275.3 1908.33   288.4 1904.71
     295 1903.74   304.8 1903.17   321.2 1903.48   328.5 1902.72   334.3 1901.27
   343.5 1902.94   367.1 1903.58   383.5 1902.85   422.8 1903.07   442.5 1904.58
   475.2 1904.02   560.4 1906.95   570.3 1907.96   612.9 1914.38   757.1 1931.64
#Mann= 3 ,-1 , 0
       0     .12       0   328.5    .045       0   343.5     .06       0
#XS Ineff= 2 , 0
                          444.41         1905.71
Permanent Ineff=
       F       F
Bank Sta=328.5,343.5
XS Rating Curve= 0 ,0
Exp/Cntr=0.3,0.1

Type RM Length L Ch R = 1 ,3461.8  ,272.4,263.2,253.8
XS GIS Cut Line= 3
     2066440.878      177449.196     2066694.351      177586.349
     2066937.406      178096.765
#Sta/Elev= 30
       0 2012.77      59 1993.25    88.4 1982.09   127.7    1970   160.5 1958.18
   193.2 1947.22   235.8 1930.96   258.7 1921.36   268.6 1916.56   275.1  1914.5
   284.9 1913.03   301.3 1913.36   330.7 1910.02   343.8 1908.23   366.6 1903.46
   379.7 1902.15   399.3 1901.22   415.6 1901.59   454.9  1901.1  491.621899.642
   500.6 1898.31   507.11899.689   513.7 1901.12  526.641902.447  548.711905.559
   650.9 1907.29   690.1 1909.23   719.6 1912.01   804.5 1924.35   853.5 1930.48
#Mann= 5 ,-1 , 0
       0     .12       0  491.62    .045       0   507.1     .06       0
  526.64     .12       0  548.71     .06       0
Bank Sta=491.62,507.1
XS Rating Curve= 0 ,0
Exp/Cntr=0.3,0.1

Type RM Length L Ch R = 1 ,3198.6  ,300.8,309.1,307.7
XS GIS Cut Line= 3
     2066279.598      177577.522      2066554.17      177799.554
     2066855.281      178100.636
#Sta/Elev= 30
       0 2013.63     6.5 2010.53    16.4 2007.38    29.4 2001.62    42.5 1996.72
      85  1984.1   137.3 1969.94   160.2 1962.68   199.4 1952.81   245.2 1943.88
   268.1 1938.23   281.2 1931.92   310.6 1914.81   323.7  1906.1   332.7 1898.33
   336.8 1897.02     340  1896.9   347.7  1898.2   356.4 1900.31  364.821900.177
   402.2 1899.55     471  1900.3   500.5 1901.85  511.461903.288  527.111904.912
   615.2 1907.65   641.4  1909.2     697 1915.34   736.3 1922.27   778.9 1927.55
#Mann= 6 ,-1 , 0
       0     .12       0   332.7    .045       0   347.7     .12       0
  364.82     .06       0  511.46     .12       0  527.11     .06       0
Bank Sta=332.7,347.7
XS Rating Curve= 0 ,0
Exp/Cntr=0.3,0.1

Type RM Length L Ch R = 1 ,2889.5  ,214.3,218,217.7
XS GIS Cut Line= 3
     2066173.056      177673.561     2066405.436      177979.172
     2066663.177      178265.787
#Sta/Elev= 30
       0  2019.1      26 2015.55    81.3 1991.87   117.1 1983.59   175.7 1965.04
   214.7 1956.08     231 1950.94   250.5  1940.1     270 1927.74   292.8  1911.3
   302.6  1906.6   309.1 1902.02   338.4 1898.85   354.6  1898.9   364.6 1896.78
   370.9 1895.66   379.6 1896.85   387.2 1898.68  399.02 1898.47  436.881898.672
   475.4 1903.47   501.5 1898.46   530.9 1900.23   560.3 1900.05   570.1 1901.55
   638.7  1905.2     655 1904.15   697.5 1912.52  738.931916.176   769.4 1916.63
#Mann= 6 ,-1 , 0
       0     .12       0   364.6    .045       0   379.6     .12       0
  399.02     .06       0  436.88     .12       0  738.93     .06       0
#XS Ineff= 2 , 0
                          472.24         1908.14
Permanent Ineff=
       F       F
Bank Sta=364.6,379.6
XS Rating Curve= 0 ,0
Exp/Cntr=0.3,0.1

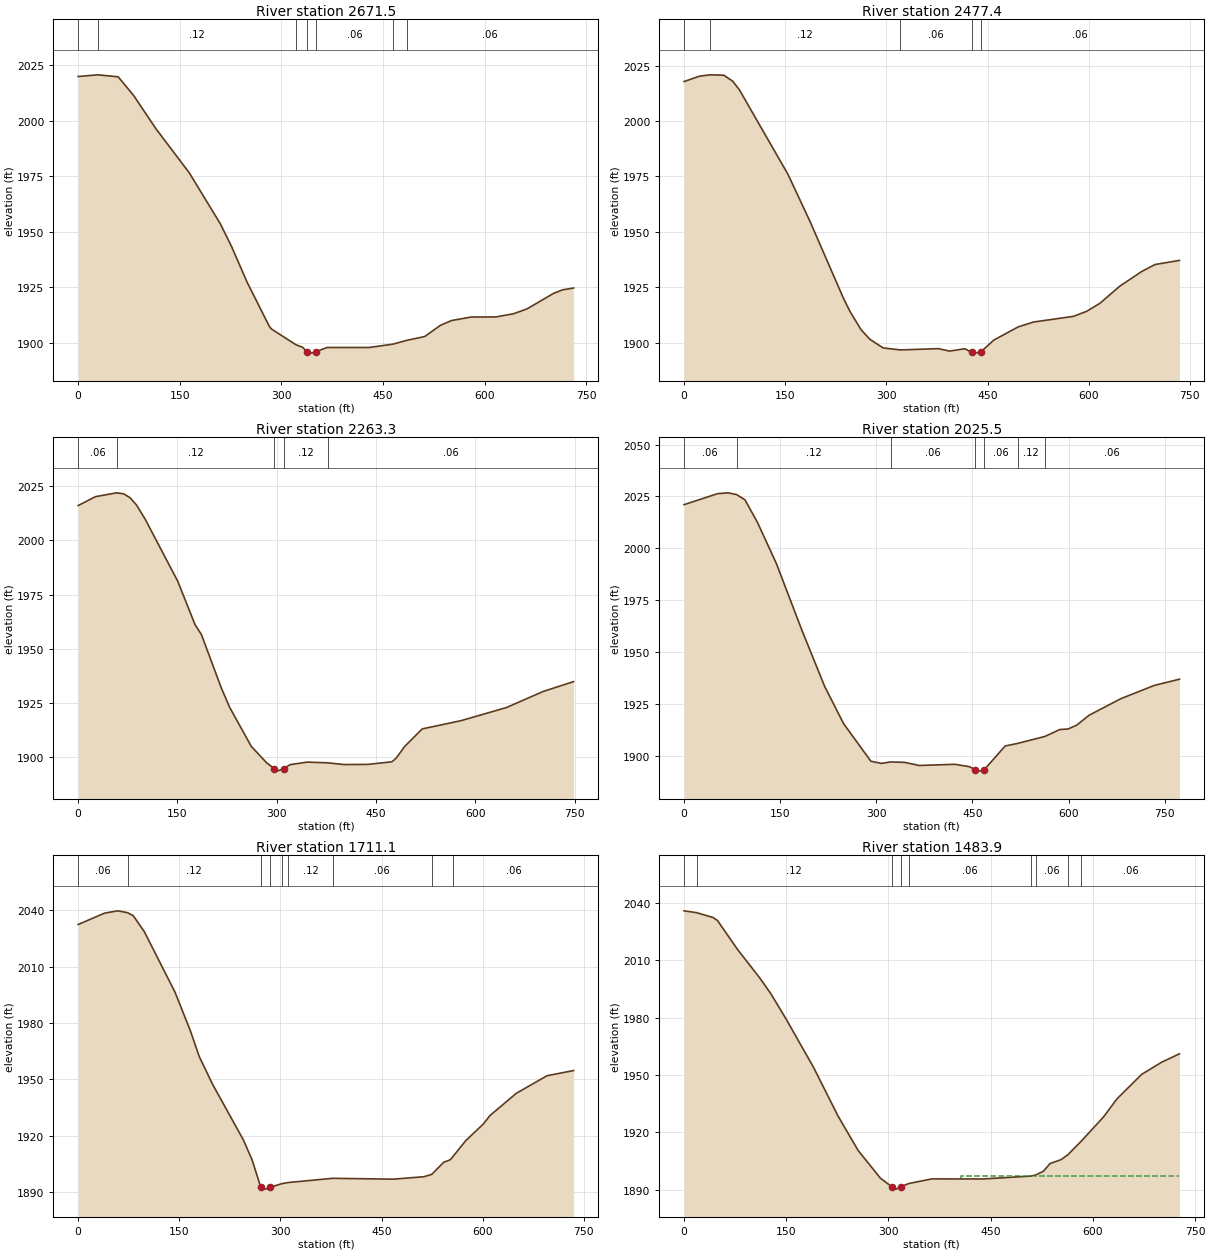
Type RM Length L Ch R = 1 ,2671.5  ,189.5,194.1,197.1
XS GIS Cut Line= 2
     2066062.406       177768.64     2066489.489       178362.39
#Sta/Elev= 30
       0 2019.78   28.812020.536      59 2019.65      82  2011.2   114.8  1996.3
     164  1976.5   209.9 1953.55   226.3 1943.46   249.3 1927.38   282.1 1907.52
   285.3 1906.29  321.331899.244   331.3 1898.07   337.8    1896   344.4 1895.44
   351.2 1896.07   367.3 1897.97   429.6 1897.98  464.621899.475  485.321901.196
   511.6  1902.9   534.6 1907.91     551 1910.08   580.5 1911.68   616.6 1911.71
   642.8 1913.14   662.5  1915.3   701.9 1922.31     715 1923.88   731.4 1924.71
#Mann= 7 ,-1 , 0
       0     .06       0   28.81     .12       0  321.33     .06       0
   337.8    .045       0   351.2     .06       0  464.62     .12       0
  485.32     .06       0
Bank Sta=337.8,351.2
XS Rating Curve= 0 ,0
Exp/Cntr=0.3,0.1

Type RM Length L Ch R = 1 ,2477.4  ,211.4,214.1,215
XS GIS Cut Line= 2
     2065980.809      177825.932      2066310.67      178482.182
#Sta/Elev= 30
       0 2017.85      23 2020.28   38.73 2020.88      59 2020.69    72.1 2018.02
      82 2014.14   154.1 1975.93   186.9 1954.58   236.1 1920.14   245.9 1914.11
   262.3 1905.86   275.4  1901.5   295.1 1897.59   320.71896.689   377.1 1897.26
   393.5 1896.17   416.4  1897.2   426.3 1895.63   429.5 1895.24   439.7  1895.7
     459 1901.08   495.1 1907.04   518.1 1909.28   577.1 1911.83   596.8  1914.1
   616.4  1917.7     646 1925.47   678.8 1932.15   698.4 1935.25   734.5  1937.1
#Mann= 5 ,-1 , 0
       0     .06       0   38.73     .12       0   320.7     .06       0
   426.3    .045       0   439.7     .06       0
Bank Sta=426.3,439.7
XS Rating Curve= 0 ,0
Exp/Cntr=0.3,0.1

Type RM Length L Ch R = 1 ,2263.3  ,235.3,237.8,237.7
XS GIS Cut Line= 2
      2065873.17      177864.127     2066152.684      178558.571
#Sta/Elev= 30
       0 2016.15    26.2 2020.26   58.132022.026    68.6 2021.58    78.4 2019.75
    88.3 2016.32   101.3 2009.79   150.4 1981.18   176.5 1961.13   186.3 1956.43
   215.8 1932.16   228.8 1922.87   261.5 1904.81   284.4 1897.28  296.231894.484
   300.7 1893.32   310.6 1894.49   320.4 1896.33   346.5  1897.5  376.821897.154
   402.1 1896.36     438 1896.44     474 1897.64   480.5 1899.32   493.6 1904.82
   519.8 1912.84   578.6 1916.66   647.2 1922.73   702.8 1930.18   748.6 1934.72
#Mann= 5 ,-1 , 0
       0     .06       0   58.13     .12       0  296.23    .045       0
   310.6     .12       0  376.82     .06       0
Bank Sta=296.23,310.6
XS Rating Curve= 0 ,0
Exp/Cntr=0.3,0.1

Type RM Length L Ch R = 1 ,2025.5  ,313.5,314.4,312.6
XS GIS Cut Line= 2
     2065701.295      177912.738     2066011.191      178621.071
#Sta/Elev= 30
       0 2021.05    52.4 2026.35    68.8 2026.75   81.892025.901      95 2023.43
   114.7  2012.4   144.2 1992.58   183.5 1960.82   219.5 1933.37     249 1915.45
   291.6 1897.33     308 1896.29  322.321896.989     344  1896.8   366.9 1895.28
   422.6 1895.86   445.6 1894.68  454.231893.297   461.9 1892.56   468.5 1893.24
   501.2 1904.69  520.521905.924   563.11909.268   586.4 1912.61   599.5  1912.9
   612.6 1914.68   632.3 1919.54   681.4 1927.45   733.8 1933.88   773.2 1936.89
#Mann= 7 ,-1 , 0
       0     .06       0   81.89     .12       0  322.32     .06       0
  454.23    .045       0   468.5     .06       0  520.52     .12       0
   563.1     .06       0
Bank Sta=454.23,468.5
XS Rating Curve= 0 ,0
Exp/Cntr=0.3,0.1

Type RM Length L Ch R = 1 ,1711.1  ,232.4,227.2,221.4
XS GIS Cut Line= 2
      2065498.17      178032.529     2065834.108      178686.175
#Sta/Elev= 30
       0 2032.39    39.2 2038.43    58.8 2039.66   73.212038.672    81.7 2037.04
      98 2028.65   143.7 1996.34   166.6 1975.66   179.6 1962.11   199.2 1947.47
     245 1917.81     258 1907.14  270.891892.567   277.6 1891.58   284.2 1892.52
   302.11894.478  311.861895.107  377.541897.336   467.1 1896.88   512.8 1898.18
  524.471899.424   542.2 1905.87     552 1907.22  556.481909.164   574.9 1917.36
     601 1926.24   610.8 1930.72     650 1942.59   695.7 1951.94   734.9 1954.68
#Mann= 9 ,-1 , 0
       0     .06       0   73.21     .12       0  270.89    .045       0
   284.2     .12       0   302.1     .06       0  311.86     .12       0
  377.54     .06       0  524.47     .12       0  556.48     .06       0
Bank Sta=270.89,284.2
XS Rating Curve= 0 ,0
Exp/Cntr=0.3,0.1

Type RM Length L Ch R = 1 ,1483.9  ,230.1,234.8,238.9
XS GIS Cut Line= 2
     2065253.378      178196.592     2065732.545      178743.467
#Sta/Elev= 30
       0 2035.72   18.322034.764    42.6 2032.23    49.1 2030.64    78.6  2015.5
   111.4 2000.53   127.7 1992.26   150.7 1978.63     190    1954     226 1928.54
   255.5 1910.58   288.2  1896.1   304.6 1891.71   311.2 1890.38     3191891.716
  329.911893.317   363.6 1895.72   438.9 1895.69  509.191897.192  515.931897.737
   527.3  1899.7   537.1 1903.71   553.5 1905.82  563.531908.417  583.161915.503
   615.7 1928.11   635.4 1937.52   671.4 1950.26   700.9 1956.66   727.1 1961.05
#Mann= 9 ,-1 , 0
       0     .06       0   18.32     .12       0   304.6    .045       0
     319     .12       0  329.91     .06       0  509.19     .12       0
  515.93     .06       0  563.53     .12       0  583.16     .06       0
#XS Ineff= 2 , 0
                          405.93         1897.47
Permanent Ineff=
       F       F
Bank Sta=304.6,319
XS Rating Curve= 0 ,0
Exp/Cntr=0.3,0.1

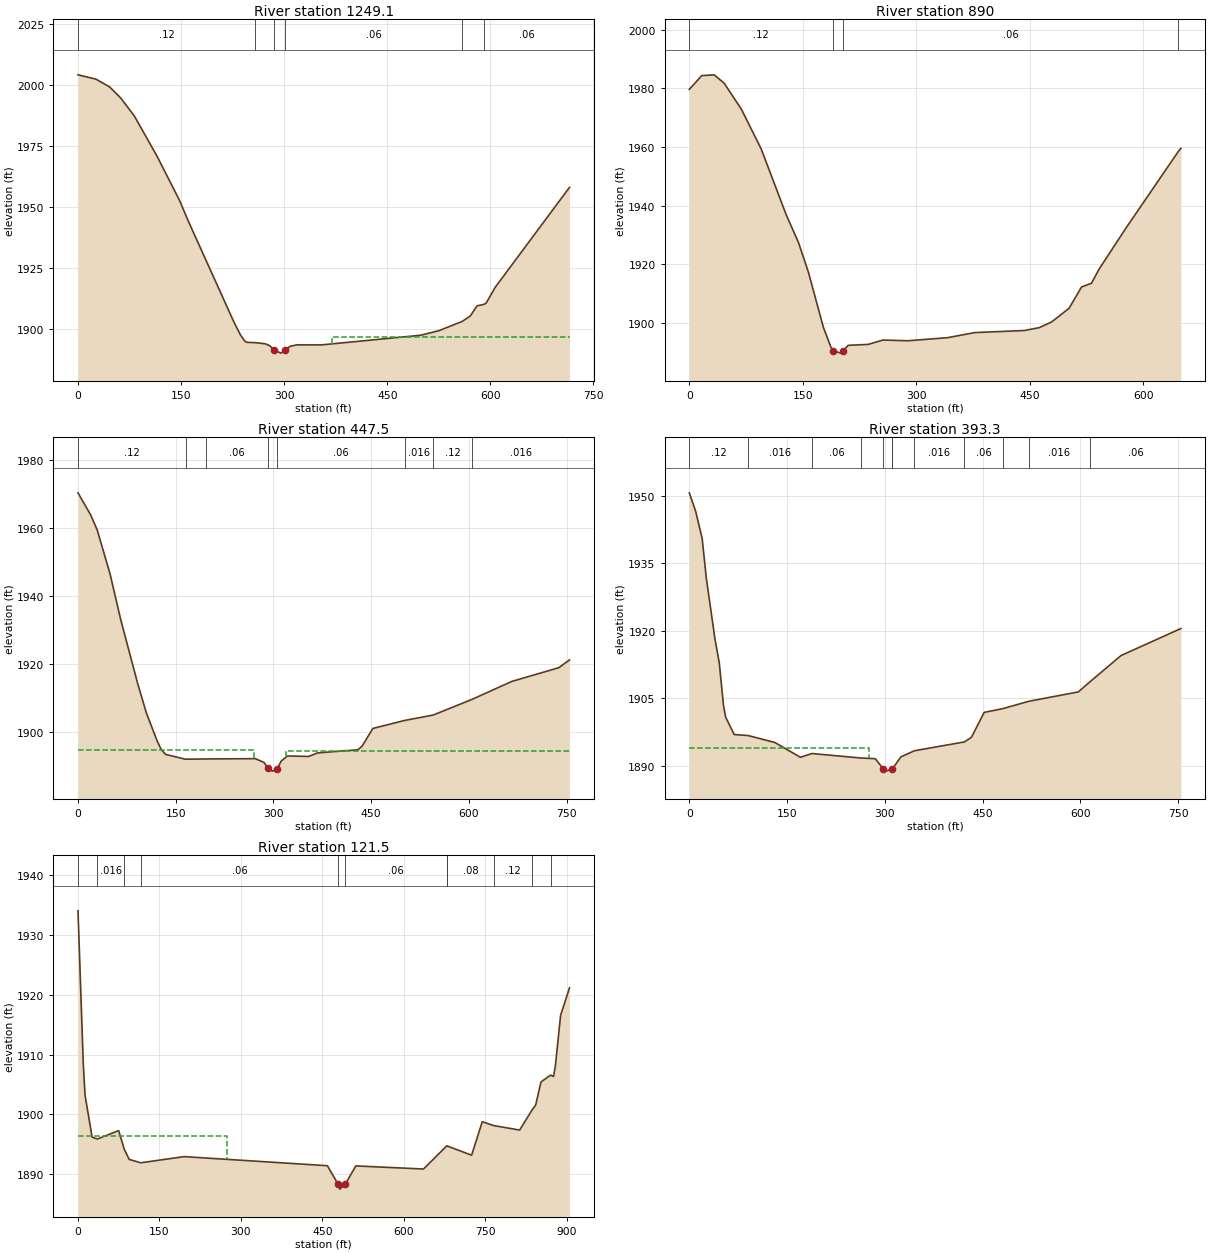
Type RM Length L Ch R = 1 ,1249.1  ,374.1,359.1,342.6
XS GIS Cut Line= 2
     2065125.774      178308.571     2065482.545      178928.363
#Sta/Elev= 30
       0  2004.3    26.2 2002.51    45.9 1999.36    62.3 1994.74      82 1987.36
   114.8 1970.95   147.6 1952.76   160.7 1944.02   226.4 1902.94   236.2 1897.45
   242.8  1894.8     246 1894.31  257.691894.192   272.3 1893.72   278.8 1892.96
   285.4 1891.12   295.2 1889.88     3011891.096   308.4 1892.65   318.2 1893.28
   354.3 1893.27   498.6 1897.23   524.9 1899.09  558.931902.907   570.8 1905.15
   580.6 1909.33  590.411909.912   593.8 1910.43   606.9  1916.9   715.1 1958.04
#Mann= 6 ,-1 , 0
       0     .12       0  257.69     .06       0   285.4    .045       0
     301     .06       0  558.93     .12       0  590.41     .06       0
#XS Ineff= 2 , 0
                          369.49         1896.69
Permanent Ineff=
       F       F
Bank Sta=285.4,301
XS Rating Curve= 0 ,0
Exp/Cntr=0.3,0.1

Type RM Length L Ch R = 1 ,890     ,425.5,442.5,457.7
XS GIS Cut Line= 2
     2064865.358      178714.821     2065472.128      178946.592
#Sta/Elev= 30
       0 1979.65    16.4 1984.32    32.8  1984.6    45.9 1981.78    68.9 1972.84
    95.1 1959.24   127.9 1936.92   144.3 1927.35   157.5 1917.14   177.1 1898.48
     187  1891.7   190.3 1890.41   200.1 1889.62   203.4 1890.44     210 1892.29
   236.2 1892.59   255.9 1894.09   288.7 1893.84   341.2 1894.89   377.2 1896.63
   442.9 1897.34   462.5 1898.32     479  1900.3   501.9 1904.95   518.3  1912.2
   531.4 1913.46   541.3 1918.21   577.4 1932.46  646.071958.403   649.5 1959.51
#Mann= 4 ,-1 , 0
       0     .12       0   190.3    .045       0   203.4     .06       0
  646.07    .016       0
Bank Sta=190.3,203.4
XS Rating Curve= 0 ,0
Exp/Cntr=0.3,0.1

Type RM Length L Ch R = 1 ,447.5   ,54.8,54.1,54
XS GIS Cut Line= 2
     2064794.611      178930.894     2065164.403      179588.447
#Sta/Elev= 30
       0 1970.41    19.7 1963.83    29.5  1959.5    49.2  1946.6    65.6 1933.14
    91.8 1914.25     105 1905.72   121.4 1897.56   127.9 1894.96   134.5 1893.56
  165.061892.153  196.971892.228   272.2 1892.31   285.4 1891.22   291.9 1889.49
   298.5 1888.65     306 1889.35   311.6 1891.54   321.4  1893.1   354.2 1892.96
   367.4 1893.99   429.7 1894.93   436.2 1896.04   452.6 1901.19  501.241903.535
  545.381905.135   605.11909.754   665.8    1915     738 1919.04   754.4 1921.33
#Mann= 8 ,-1 , 0
       0     .12       0  165.06    .016       0  196.97     .06       0
   291.9    .045       0     306     .06       0  501.24    .016       0
  545.38     .12       0   605.1    .016       0
#XS Ineff= 2 , 0
          270.68 1894.93  319.53         1894.51
Permanent Ineff=
       F       F
Bank Sta=291.9,306
XS Rating Curve= 0 ,0
Exp/Cntr=0.3,0.1

Type RM Length L Ch R = 1 ,393.3   ,279.1,271.9,264.5
XS GIS Cut Line= 2
     2064746.434      178954.332     2065116.226      179611.884
#Sta/Elev= 30
       0 1950.62     9.8  1946.5    19.7  1940.5    26.2 1931.57    39.4 1918.16
    45.9 1912.99    52.5  1903.4    55.8 1900.85    68.9    1897      901896.781
   131.2 1895.24   170.6 1891.95  188.131892.782  263.091891.794   285.4 1891.64
   297.71889.381   301.8 1888.88   311.6 1889.35  311.621889.352   324.7 1892.04
  345.481893.399  422.241895.358     433 1896.38   452.6 1901.91  481.07 1902.74
  521.251904.383     597 1906.45  615.011908.706   662.6 1914.52   754.4 1920.51
#Mann= 12 ,-1 , 0
       0     .12       0      90    .016       0  188.13     .06       0
  263.09    .016       0   297.7    .045       0   311.6    .016       0
  311.62     .08       0  345.48    .016       0  422.24     .06       0
  481.07     .08       0  521.25    .016       0  615.01     .06       0
#XS Ineff= 2 , 0
          275.77 1893.98
Permanent Ineff=
       F       F
Bank Sta=297.7,311.6
XS Rating Curve= 0 ,0
Exp/Cntr=0.3,0.1

Type RM Length L Ch R = 1 ,121.5   ,117.7,121.5,125.3
XS GIS Cut Line= 3
     2064742.962      178964.821     2064662.233      179373.675
     2065024.212        179701.8
#Sta/Elev= 30
       0 1934.03     9.8 1908.38      13 1903.22      26 1896.22   35.591895.905
    74.9 1897.31    85.51894.129    94.4 1892.49  115.61 1891.93   195.4 1892.96
   459.4 1891.44     479 1888.36   482.3 1887.53   492.4 1888.37   511.8 1891.41
   636.4 1890.89  679.381894.768  680.151894.734     725  1893.2   744.6 1898.79
  765.521898.152   813.5  1897.4  836.111900.727     843 1901.59   852.8 1905.44
  870.341906.573   875.8 1906.36   879.1 1907.97   888.9 1916.58   905.3 1921.17
#Mann= 11 ,-1 , 0
       0     .12       0   35.59    .016       0    85.5     .12       0
  115.61     .06       0     479    .045       0   492.4     .06       0
  679.38     .12       0  680.15     .08       0  765.52     .12       0
  836.11    .016       0  870.34     .06       0
#XS Ineff= 2 , 0
          274.51 1896.42
Permanent Ineff=
       F       F
Bank Sta=479,492.4
XS Rating Curve= 0 ,0
Exp/Cntr=0.3,0.1

Chan Stop Cuts=-1
Use User Specified Reach Order=0
Composite Channel Slope=5